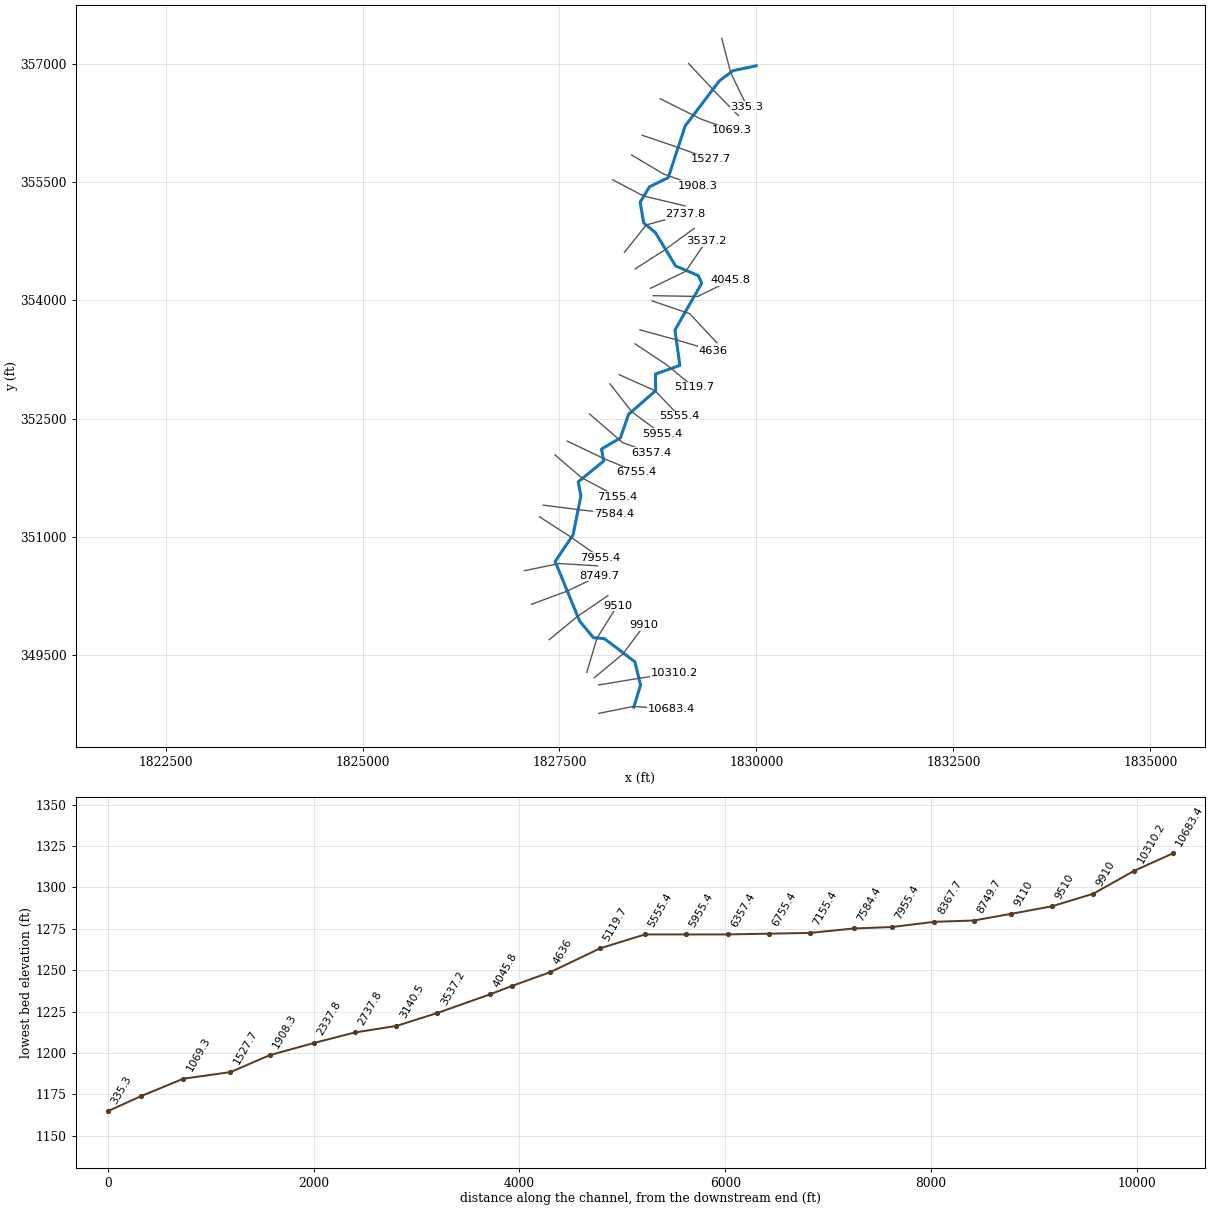
--- LrlRn4.prj (project) ---

Proj Title=LrlRn4
Current Plan=p01
Default Exp/Contr=0,0
English Units
Geom File=g01
Flow File=f01
Plan File=p01
BEGIN DESCRIPTION:
END DESCRIPTION:
DSS Export Rating Curves= 0
DSS Export Rating Curve Sorted= 0
DSS Export Volume Flow Curves= 0
DXF OffsetX= 0
DXF OffsetY= 0
DXF ScaleX= 0
DXF ScaleY= 0

--- LrlRn4.p01 (plan) ---

Plan Title=Floodplain
Program Version=4.00
Geom File=g01
Flow File=f01
K Sum by GR=0
Std Step Tol=0.01
Critical Tol=0.01
Num of Std Step Trials=20
Max Error Tol=0.3
Flow Tol Ratio=0.001
Split Flow NTrial=30
Split Flow Tol=0.02
Split Flow Ratio=0.02
Log Output Level=0
Friction Slope Method=1
Unsteady Friction Slope Method=2
Unsteady Bridges Friction Slope Method=1
Global Log Level=0
CheckData=False
Run HTab=0
Run UNet=0
Run PostProcess=0
UNET Theta=0
UNET Theta Warmup=0
UNET ZTol=0
UNET ZSATol=0
UNET MxIter=0
UNET MaxInSteps=0
UNET DtIC=0
UNET DtMin=0
UNET MaxCRTS=0
UNET WFStab=0
UNET SFStab=0
UNET WFX=0
UNET SFX=0
UNET DSS MLevel=0
UNET DZMax Abort=0
UNET Convert EG Bridges=0
UNET Use Existing IB Tables=0
UNET Froude Limit=0
UNET Froude Power=0
Write IC File=0
Echo Input=False
Echo Output=False
Write Detailed=0

--- LrlRn4.f01 (steady flow) ---

Flow Title=NFF Regression Equation
Program Version=4.00
Number of Profiles=1
Profile Names=P100yr
River Rch & RM=LrlRn4,Main      ,10683.4
726.2800
River Rch & RM=LrlRn4,Main      ,9910
730.5429
River Rch & RM=LrlRn4,Main      ,9910
940.2714
River Rch & RM=LrlRn4,Main      ,8367.7
1030.433
River Rch & RM=LrlRn4,Main      ,7584.4
1105.908
River Rch & RM=LrlRn4,Main      ,5955.4
1159.500
River Rch & RM=LrlRn4,Main      ,3537.2
1267.767
River Rch & RM=LrlRn4,Main      ,335.3
1405.715
Boundary for River Rch & Prof#=LrlRn4,Main      ,1
Up Type=0
Dn Type=3
Dn Slope=0.018452

--- LrlRn4.g01 (geometry) ---

Geom Title=USGS 3m DEM
Program Version=4.00

River Reach=LrlRn4          ,Main
Reach XY= 30
     1828443.313      348839.562     1828528.911      349119.988
     1828457.053      349414.919      1828070.62      349708.608
     1827931.503      349720.631      1827756.32      349930.164
     1827445.138      350687.334     1827672.163        351024.2
     1827771.777      351517.118     1827737.428      351697.454
     1828062.032      351961.946     1828032.835      352113.085
     1828273.283      352253.918     1828376.332      352552.761
     1828721.546      352855.038     1828718.111      353064.571
     1829028.129      353173.469     1828965.549      353622.908
     1829305.473      354215.996     1829262.804      354312.711
     1828974.083      354435.026     1828718.111      354857.623
      1828568.69      354981.282     1828524.035      355245.774
     1828644.115      355440.574     1828880.213      355555.778
     1829094.976      356210.025      1829528.77      356781.779
     1829703.709      356912.628     1829995.918      356973.563

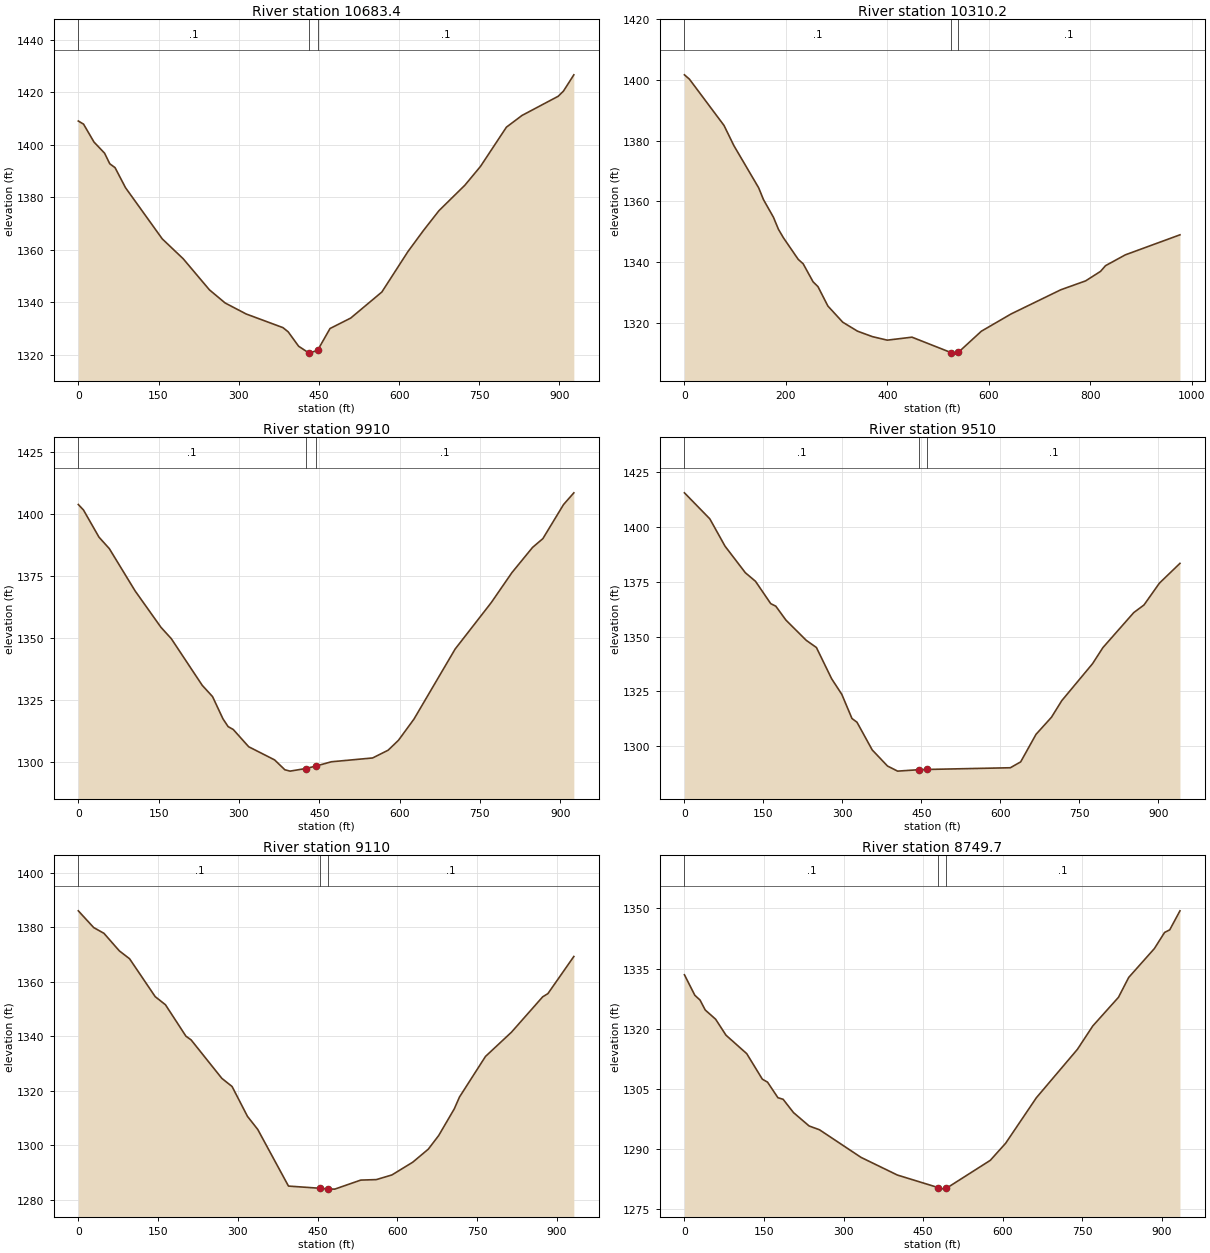
Type RM Length L Ch R = 1 ,10683.4 ,373.222,373.2,378.155
XS GIS Cut Line= 3
     1827998.744      348760.846     1828441.352      348849.368
     1828915.697      348815.526
#Sta/Elev= 30
       0 1409.08     9.8 1407.89    29.4 1401.04    49.1 1396.82    58.9 1392.76
    68.7 1391.31    88.3 1383.64     157 1364.13   196.2 1356.54   245.3 1344.68
   274.7 1339.67     314 1335.48   382.7 1330.28   392.5 1328.69   412.1 1323.18
   431.7 1320.55   447.6 1321.61   470.8 1329.93   509.6 1333.93   567.8 1343.86
   616.4 1359.23   645.5  1367.3   674.6 1374.88   723.1  1384.6   752.2 1391.74
   800.8 1406.74   829.9  1411.2   897.8 1418.54   907.5  1420.5   926.9  1426.7
#Mann= 3 , 0 , 0
       0      .1       0   431.7    .045       0   447.6      .1       0
Bank Sta=431.7,447.6
XS Rating Curve= 0 ,0
Exp/Cntr=0.3,0.1

Type RM Length L Ch R = 1 ,10310.2 ,387.92,400.18,418.442
XS GIS Cut Line= 3
     1827995.609      349121.014      1828524.78      349208.762
     1828960.987      349271.077
#Sta/Elev= 30
       0 1401.69     9.8 1400.27      78 1385.03    97.5 1378.38   146.3 1364.51
     156 1360.56   175.5 1354.81   185.3 1350.86   195.1 1348.07   224.3 1340.96
   234.1 1339.49   253.6 1333.57   263.3 1331.97   282.8  1325.6   312.1 1320.27
   341.3 1317.31   370.6 1315.52   399.9 1314.36   448.6 1315.34   525.3 1310.29
   536.4 1310.09   540.3 1310.39   585.4  1317.3   644.1 1322.99     742 1330.94
     791 1333.87   820.4    1337   830.2 1338.87   869.3 1342.44     977 1349.03
#Mann= 3 , 0 , 0
       0      .1       0   525.3    .045       0   540.3      .1       0
Bank Sta=525.3,540.3
XS Rating Curve= 0 ,0
Exp/Cntr=0.3,0.1

Type RM Length L Ch R = 1 ,9910    ,386.09,400,401.714
XS GIS Cut Line= 3
     1827941.733      349213.286     1828305.561      349514.804
     1828575.916      349878.005
#Sta/Elev= 30
       0 1403.65     9.6 1401.45    38.6 1390.49    57.9 1385.86   106.1  1368.8
   154.3 1354.15   173.6 1349.57   231.4 1330.75   250.7 1326.19     270 1317.29
   279.7 1314.11   289.3 1312.95   318.2 1305.98   366.5 1300.69   385.7 1296.71
   395.4 1296.16   424.3 1297.19   443.6 1298.19   472.5 1299.93   549.6 1301.47
   578.5 1304.59   597.8 1308.59   626.7 1317.11   703.7 1345.39   771.2 1364.14
   809.7 1376.19   848.2 1386.35   867.5  1389.9     906 1403.61   925.3 1408.36
#Mann= 3 , 0 , 0
       0      .1       0   424.3    .045       0   443.6      .1       0
Bank Sta=424.3,443.6
XS Rating Curve= 0 ,0
Exp/Cntr=0.3,0.1

Type RM Length L Ch R = 1 ,9510    ,413.344,400,391.01
XS GIS Cut Line= 3
     1827846.598      349280.098     1827975.845      349714.423
      1828234.43      350128.488
#Sta/Elev= 30
       0 1415.54    48.2 1403.67    77.1 1391.21   115.7 1379.09     135 1375.18
   163.9    1365   173.5 1363.85   192.8 1357.49   231.4 1348.26   250.7 1344.99
   279.6 1330.74   298.9 1323.64   318.2 1312.63   327.8  1310.9   356.7 1298.28
   385.7 1290.94   404.9 1288.61   445.6 1289.26   460.6 1289.37   619.1 1290.15
   638.7 1292.83   667.9  1305.4   697.2 1313.18   716.8 1320.76   775.3 1337.63
   794.9 1344.94   853.5 1360.91     873  1364.4   902.3 1374.36   941.3 1383.37
#Mann= 3 , 0 , 0
       0      .1       0   445.6    .045       0   460.6      .1       0
Bank Sta=445.6,460.6
XS Rating Curve= 0 ,0
Exp/Cntr=0.3,0.1

Type RM Length L Ch R = 1 ,9110    ,367.632,360.383,356.917
XS GIS Cut Line= 3
     1827370.092      349695.761     1827727.157      349989.815
     1828114.641      350254.132
#Sta/Elev= 30
       0 1385.98    28.9 1379.85    48.2 1377.74    77.1 1371.31    96.4 1368.41
   144.6 1354.52   163.8 1351.57   202.4 1340.03     212  1338.7   269.8  1324.6
   289.1  1321.6     318 1310.67   337.3 1305.88   395.1 1285.12   455.1  1284.3
   470.1 1284.06   482.1    1284     531 1287.31   560.3 1287.49   589.6  1289.2
   628.7 1293.86     658 1298.65   677.5 1303.63   706.9 1313.44   716.6 1317.75
   765.5 1332.62   814.3  1341.5     873 1354.46   882.8 1355.63   931.6 1369.25
#Mann= 3 , 0 , 0
       0      .1       0   455.1    .045       0   470.1      .1       0
Bank Sta=455.1,470.1
XS Rating Curve= 0 ,0
Exp/Cntr=0.3,0.1

Type RM Length L Ch R = 1 ,8749.7  ,385.853,381.962,376.395
XS GIS Cut Line= 3
     1827144.892      350144.318     1827595.176      350310.548
     1828004.891      350507.319
#Sta/Elev= 30
       0 1333.46    19.6 1328.35    29.4 1327.16    39.2 1324.68    58.8 1322.38
    78.4 1318.39   117.5 1313.79   146.9 1307.43   156.7 1306.69   176.3 1302.81
   186.1 1302.41   205.7 1299.09   235.1 1295.76   254.7 1294.81   333.1 1287.92
   401.6 1283.52   478.4  1280.4   489.7 1280.01   493.4 1280.17   576.7 1287.18
   605.7 1291.44   663.7  1302.8   741.1 1314.87   770.1  1320.7   818.5 1327.84
   837.8 1332.79   886.2 1339.99   905.5 1344.02   915.2 1344.67   934.5 1349.41
#Mann= 3 , 0 , 0
       0      .1       0   478.4    .045       0   493.4      .1       0
Bank Sta=478.4,493.4
XS Rating Curve= 0 ,0
Exp/Cntr=0.3,0.1

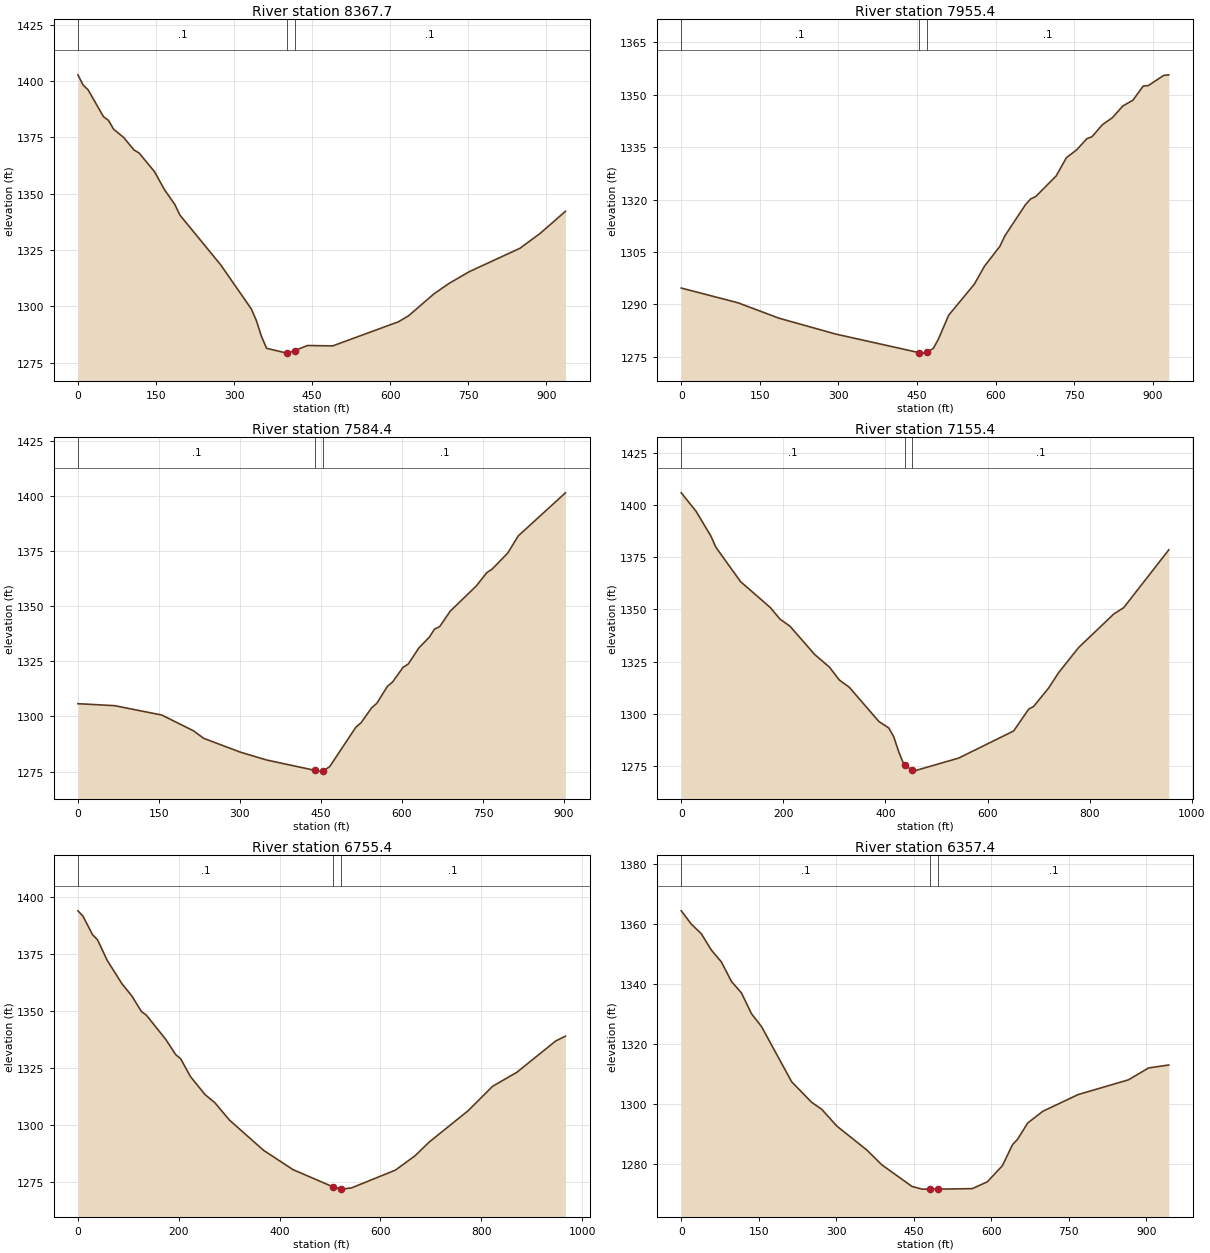
Type RM Length L Ch R = 1 ,8367.7  ,429.218,412.266,394.164
XS GIS Cut Line= 3
     1827054.504      350570.322     1827496.007      350661.263
     1827981.281      350632.497
#Sta/Elev= 30
       0  1402.7     9.8 1398.24    19.6 1396.04      49 1384.16    58.8 1382.46
    68.6 1378.58    88.2 1374.84   107.8 1369.35   117.6 1368.01     147 1359.79
   166.6 1351.65   186.2 1345.19     196 1340.48   274.4 1318.39   333.2 1298.84
     343 1293.63   352.8  1286.6   362.6 1281.36   401.7 1279.22   416.7 1280.31
     441  1282.6   489.7 1282.43   616.1 1293.14   635.5  1295.8   684.1  1305.5
   713.3 1310.16   752.2 1315.37   849.4 1325.73   888.3 1332.34   936.9 1342.14
#Mann= 3 , 0 , 0
       0      .1       0   401.7    .045       0   416.7      .1       0
Bank Sta=401.7,416.7
XS Rating Curve= 0 ,0
Exp/Cntr=0.3,0.1

Type RM Length L Ch R = 1 ,7955.4  ,360.716,371.011,382.399
XS GIS Cut Line= 3
     1827245.832      351253.766     1827634.197      351004.101
     1828018.342      350735.033
#Sta/Elev= 30
       0  1294.7   108.1 1290.49   186.6 1286.07   294.7 1281.54   454.2 1276.21
   461.7 1276.08   469.2 1276.36   481.2 1277.44     491 1280.13   510.5 1286.93
   559.4  1295.8   578.9 1300.96   608.3 1306.65     618  1309.7   657.1 1318.55
   666.9 1320.18   676.7 1320.89   715.7 1326.78   735.3 1332.01   754.8 1334.24
   774.4 1337.44   784.1 1337.99   803.7  1341.4   823.2 1343.46   842.8 1346.77
   862.3 1348.45   881.8 1352.49   891.6 1352.63   920.9 1355.53   930.7  1355.7
#Mann= 3 , 0 , 0
       0      .1       0   454.2    .045       0   469.2      .1       0
Bank Sta=454.2,469.2
XS Rating Curve= 0 ,0
Exp/Cntr=0.3,0.1

Type RM Length L Ch R = 1 ,7584.4  ,444.042,428.989,417.637
XS GIS Cut Line= 3
     1827293.623      351401.754     1827775.404      351340.923
     1828189.851      351293.938
#Sta/Elev= 30
       0 1305.81      68 1304.91   155.4 1300.65   213.7 1293.53   233.1 1290.06
   301.1 1283.78   349.6 1280.23   439.3 1275.52   446.8 1275.19   454.3  1275.3
   466.2 1277.25   514.7 1295.15   524.4 1297.19   543.8 1303.93   553.5 1305.99
   572.9 1313.65   582.6 1315.62     602 1322.33   611.7 1323.82   631.1 1331.05
   650.5 1335.97   660.2 1339.63   669.9 1340.82   689.3 1347.79   737.8  1359.3
   757.2 1365.32   766.9 1366.89     796 1374.24   815.4    1382   902.7 1401.54
#Mann= 3 , 0 , 0
       0      .1       0   439.3    .045       0   454.3      .1       0
Bank Sta=439.3,454.3
XS Rating Curve= 0 ,0
Exp/Cntr=0.3,0.1

Type RM Length L Ch R = 1 ,7155.4  ,393.396,400,402.289
XS GIS Cut Line= 3
     1827443.257      352038.676     1827781.758      351749.312
     1828232.481      351511.044
#Sta/Elev= 30
       0 1405.86      29 1397.01    58.1 1385.11    67.8 1379.78   116.2  1363.3
   174.3 1350.93   193.6  1345.3     213 1341.95   261.4 1328.39   290.4 1322.31
   309.8 1316.15   329.2  1312.7   387.2 1296.28   406.6 1293.19   416.3 1288.96
     426 1281.82   435.6 1276.01   437.8 1275.52   452.8 1272.82   455.1  1272.5
   543.4 1278.74   651.2 1291.74   680.6 1302.18   690.4  1303.5   719.8 1312.35
   739.5 1319.74   778.7 1331.77   847.3 1347.77   866.9 1350.85   955.2 1378.54
#Mann= 3 , 0 , 0
       0      .1       0   437.8    .045       0   452.8      .1       0
Bank Sta=437.8,452.8
XS Rating Curve= 0 ,0
Exp/Cntr=0.3,0.1

Type RM Length L Ch R = 1 ,6755.4  ,405.074,398.044,387.305
XS GIS Cut Line= 3
      1827598.58      352213.662     1828062.734      351992.818
     1828481.457      351820.007
#Sta/Elev= 30
       0 1393.75     9.7 1391.52    29.1 1383.29    38.8 1381.15    58.2 1372.05
    87.3 1361.89   106.7  1356.6   126.1 1349.69   135.8 1348.13   174.6 1337.43
     194 1330.86   203.7 1329.11   223.1 1321.32   252.2 1313.38   271.6 1309.87
   300.6 1302.25   368.5 1288.99   426.7 1280.58   506.5    1273   521.5 1272.15
   523.7 1272.06   542.9 1272.61   629.7 1280.37   668.2 1286.55   697.1 1292.71
   774.2 1306.38   822.4    1317   870.6 1323.14   947.7 1336.84     967 1338.95
#Mann= 3 , 0 , 0
       0      .1       0   506.5    .045       0   521.5      .1       0
Bank Sta=506.5,521.5
XS Rating Curve= 0 ,0
Exp/Cntr=0.3,0.1

Type RM Length L Ch R = 1 ,6357.4  ,406.397,401.956,403.82
XS GIS Cut Line= 3
     1827882.635      352557.197     1828300.982      352194.988
       1828668.4      352063.593
#Sta/Elev= 30
       0 1364.51    19.4 1360.09    38.8 1356.86    58.2 1351.42    77.7 1347.44
    97.1 1340.94   116.5  1337.1   135.9 1330.16   155.3 1325.87   213.6 1307.46
   252.4 1300.57   271.8 1298.27     301 1292.67   359.2 1284.65   388.3  1279.7
   446.6  1272.5     466  1271.6     482  1271.6     497  1271.6   563.1 1271.76
   592.4 1274.04   621.6 1279.45   641.2 1286.47   650.9 1288.24   670.4 1293.66
   699.7 1297.58     768 1303.16   865.5 1308.09   904.5 1312.06   943.6 1313.04
#Mann= 3 , 0 , 0
       0      .1       0     482    .045       0     497      .1       0
Bank Sta=482,497
XS Rating Curve= 0 ,0
Exp/Cntr=0.3,0.1

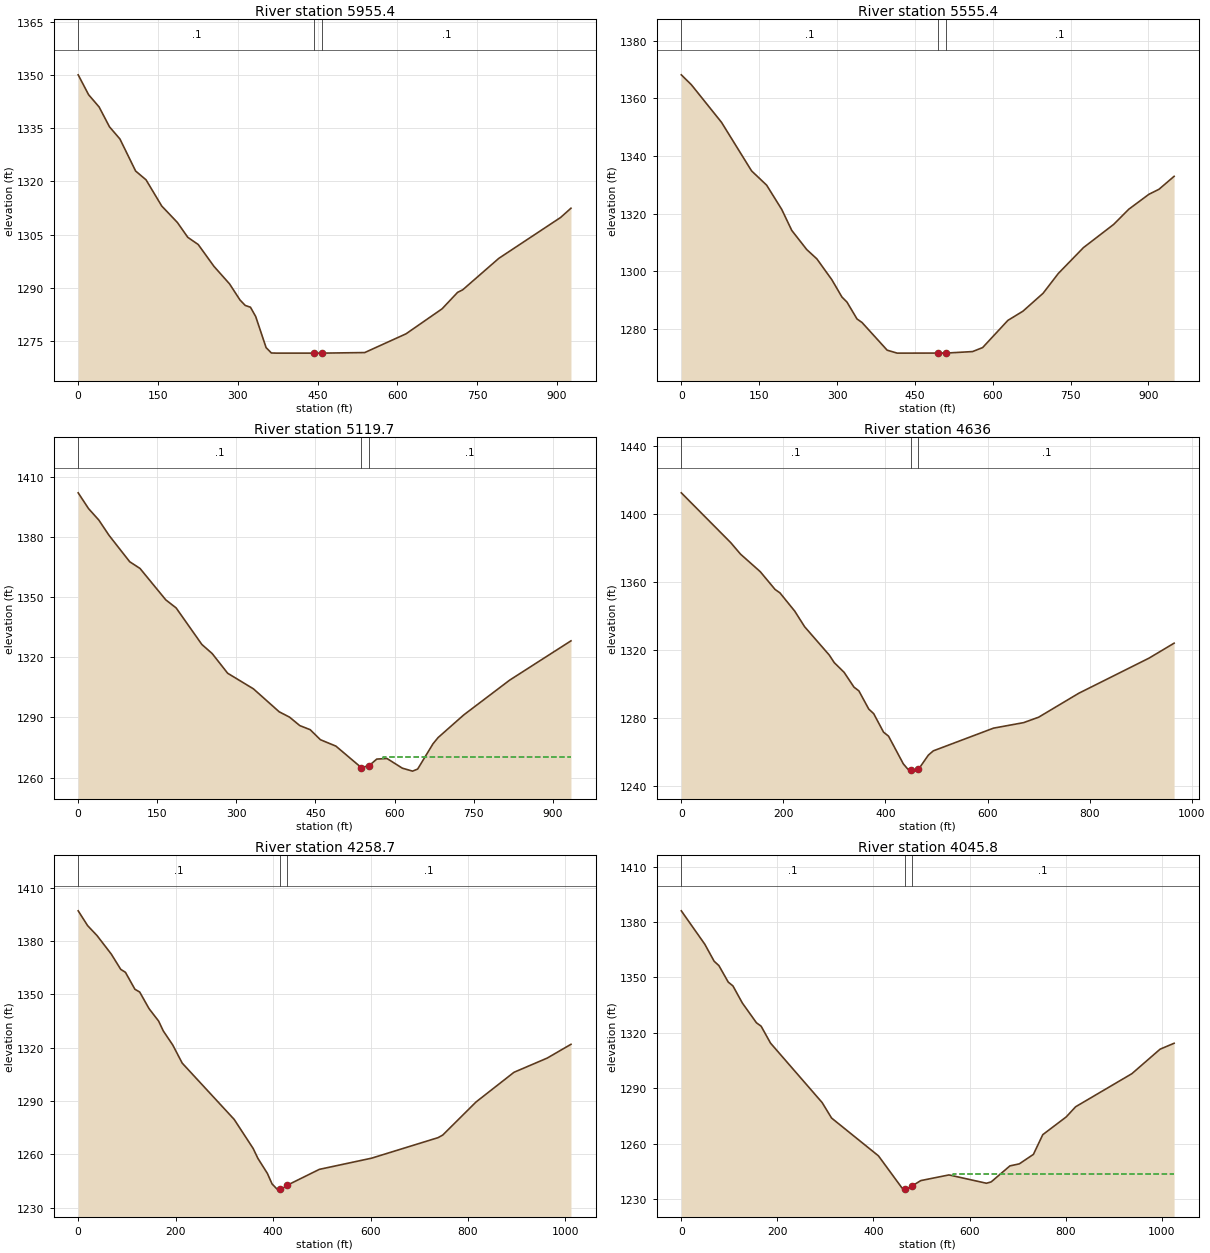
Type RM Length L Ch R = 1 ,5955.4  ,388.616,400,395.833
XS GIS Cut Line= 3
     1828139.985      352941.064     1828418.019      352585.344
       1828800.6      352303.969
#Sta/Elev= 30
       0 1350.05    19.6 1344.44    39.3    1341    58.9 1335.38    78.5 1331.96
     108 1322.93   127.6 1320.45     157 1313.08   186.5 1308.43   206.1 1304.24
   225.7 1302.21   255.2 1296.07   284.6 1291.11   304.3 1286.56   314.1 1285.04
   323.9 1284.54   333.7 1281.92   353.3 1273.15   363.2 1271.64     373  1271.6
     444  1271.6     459  1271.6   538.7 1271.76   616.3 1277.04   684.1 1284.09
   713.2 1288.72   722.9 1289.45   790.7 1298.31     907 1309.85   926.4 1312.45
#Mann= 3 , 0 , 0
       0      .1       0     444    .045       0     459      .1       0
Bank Sta=444,459
XS Rating Curve= 0 ,0
Exp/Cntr=0.3,0.1

Type RM Length L Ch R = 1 ,5555.4  ,437.061,435.722,443.629
XS GIS Cut Line= 3
     1828258.113      353056.868     1828716.869      352850.607
     1829023.968      352526.447
#Sta/Elev= 30
       0 1368.22    19.3  1364.8    77.4 1351.74   135.4 1334.86   164.4 1329.91
   193.5 1321.49   212.8  1314.2   241.8 1307.52   261.2 1304.31   290.2 1297.03
   309.5 1291.06   319.2 1289.31   338.6 1283.43   348.2 1282.22   396.6 1272.61
   415.9 1271.58   495.5  1271.6   510.5  1271.6   561.2 1272.12   580.6 1273.51
   629.2 1282.94   658.3 1286.15   697.1 1292.37   726.3 1299.22   774.8 1308.21
     833 1316.27   862.2 1321.55     901 1326.74   920.4 1328.48   949.5 1332.97
#Mann= 3 , 0 , 0
       0      .1       0   495.5    .045       0   510.5      .1       0
Bank Sta=495.5,510.5
XS Rating Curve= 0 ,0
Exp/Cntr=0.3,0.1

Type RM Length L Ch R = 1 ,5119.7  ,477.214,483.699,489.377
XS GIS Cut Line= 3
     1828458.916      353447.881     1828857.927      353182.743
     1829210.587      352894.257
#Sta/Elev= 30
       0 1402.08    19.6 1394.23    39.1 1388.51    58.7  1380.8    97.8 1367.68
   117.3 1364.34   166.2 1348.66   185.8 1344.65   234.6 1326.41   254.2 1321.87
   283.5 1312.06   332.4 1304.27   381.3 1292.81   400.9 1290.15   420.4 1285.92
     440  1283.9   459.5 1278.88   488.8  1275.7     537 1264.97     552 1265.97
   566.3 1269.22   585.7 1269.52   614.8 1264.69   634.2 1263.21   643.9 1264.24
     673 1276.84   682.6 1279.93   731.1 1291.21   818.4 1308.61   934.7 1328.22
#Mann= 3 , 0 , 0
       0      .1       0     537    .045       0     552      .1       0
#XS Ineff= 2 , 0
                           577.5         1270.15
Permanent Ineff=
       F       F
Bank Sta=537,552
XS Rating Curve= 0 ,0
Exp/Cntr=0.3,0.1

Type RM Length L Ch R = 1 ,4636    ,378.351,377.263,376.405
XS GIS Cut Line= 3
      1828519.89      353624.745     1828948.934      353508.029
     1829448.728      353360.882
#Sta/Elev= 30
       0 1412.47    96.7 1383.23     116 1376.43   154.7 1366.11   183.7 1355.67
   193.3 1353.64   222.3 1342.89   241.6 1333.75     290 1317.05   299.6 1312.66
     319 1306.92   338.3 1298.23     348    1296   367.3 1285.32     377 1282.61
   396.3 1271.73     406 1269.42     435 1253.12   444.6 1249.74   449.6 1249.28
   454.5 1248.83   464.6 1249.83     484 1258.22   493.8 1260.75   611.8 1274.11
   670.7 1277.34   700.2 1280.54   778.9 1294.63   916.5 1315.27   965.6 1324.06
#Mann= 3 , 0 , 0
       0      .1       0   449.6    .045       0   464.6      .1       0
Bank Sta=449.6,464.6
XS Rating Curve= 0 ,0
Exp/Cntr=0.3,0.1

Type RM Length L Ch R = 1 ,4258.7  ,205.235,212.97,220.705
XS GIS Cut Line= 3
     1828674.626      353992.585     1829152.387      353830.168
     1829498.991      353460.528
#Sta/Elev= 30
       0 1397.12    19.4 1388.78    38.8 1383.15    67.9 1372.77    87.3 1364.18
      97 1362.49   116.4 1352.95   126.2  1351.4   145.6 1341.96     165 1335.06
   174.7 1329.46   194.1 1321.55   213.5 1311.35   320.2 1279.63   359.1 1263.27
   368.8 1257.71   388.2 1249.27   397.9 1243.31   407.6 1240.54   414.5 1240.42
   417.3 1240.38   429.5 1242.64   494.9 1251.51   602.1 1257.81   738.5 1269.37
   748.2 1270.84   816.4 1289.44   894.4 1306.19   962.6 1314.19  1011.3 1321.95
#Mann= 3 , 0 , 0
       0      .1       0   414.5    .045       0   429.5      .1       0
Bank Sta=414.5,429.5
XS Rating Curve= 0 ,0
Exp/Cntr=0.3,0.1

Type RM Length L Ch R = 1 ,4045.8  ,512.609,508.529,531.138
XS GIS Cut Line= 3
     1828689.257      354058.544     1829256.122      354048.761
      1829667.73      354251.882
#Sta/Elev= 30
       0 1386.02    48.9 1367.94    68.4  1358.7    78.2 1356.38    97.7 1347.43
   107.5 1345.35   127.1 1336.09   156.4  1325.4   166.2 1323.54   185.7  1314.4
   293.2 1282.18   312.8 1273.81   410.5 1253.31   459.4 1235.94     466 1235.52
   469.2 1235.31     481  1237.1   498.5 1239.93   557.2    1243   635.3 1238.49
   645.1 1239.23   684.1 1247.89   703.7    1249     733 1254.12   752.5  1264.8
   801.3 1274.41   820.9 1279.91   938.1 1297.84   996.7 1311.09  1025.9  1314.3
#Mann= 3 , 0 , 0
       0      .1       0     466    .045       0     481      .1       0
#XS Ineff= 2 , 0
                          565.46         1243.76
Permanent Ineff=
       F       F
Bank Sta=466,481
XS Rating Curve= 0 ,0
Exp/Cntr=0.3,0.1

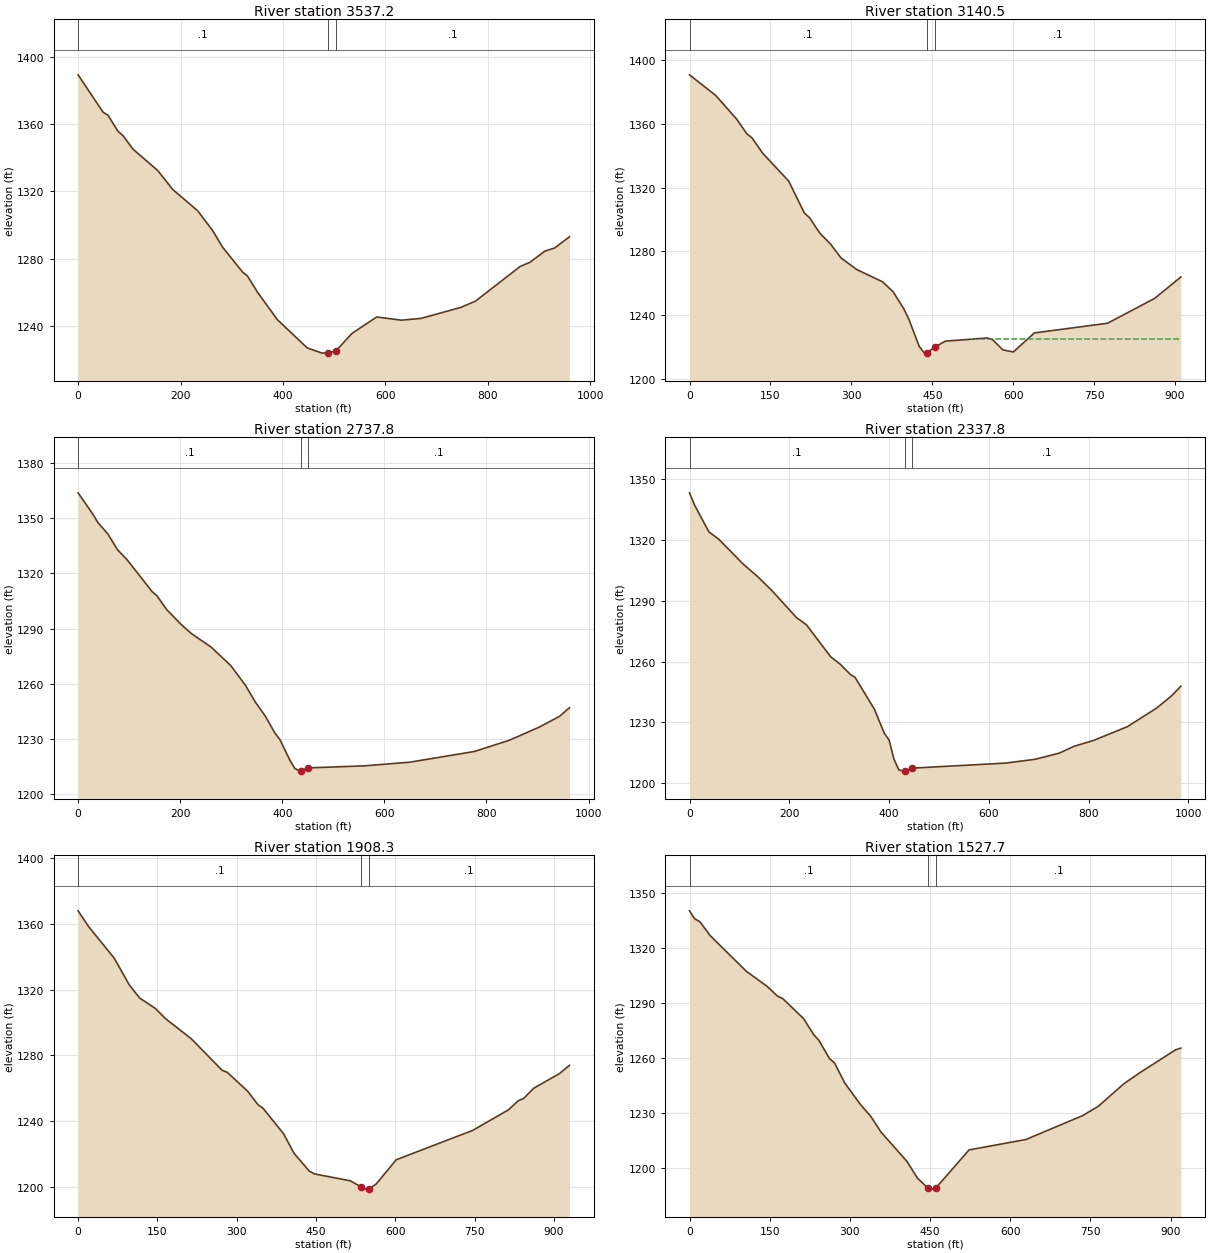
Type RM Length L Ch R = 1 ,3537.2  ,378.252,396.778,389.519
XS GIS Cut Line= 3
     1828654.676      354151.646      1829101.63      354367.142
     1829362.867      354749.954
#Sta/Elev= 30
       0 1389.15    48.6 1367.05    58.4 1365.19    77.8 1355.68    87.6 1353.13
     107 1345.14   155.7 1332.33   184.9 1321.12   233.5 1308.54   262.7 1296.81
   282.1 1287.01   321.1 1272.23   330.8 1269.85   350.3 1260.28   389.2 1243.94
   447.5 1227.22   476.7 1224.12   488.7  1224.3   503.7  1225.5   534.8 1235.79
   583.1 1245.55   631.4 1243.66     670 1244.72   747.2 1251.22   776.2 1254.97
   863.1 1275.47   882.4 1277.98   911.4 1284.57   930.7 1286.46   959.6 1293.09
#Mann= 3 , 0 , 0
       0      .1       0   488.7    .045       0   503.7      .1       0
Bank Sta=488.7,503.7
XS Rating Curve= 0 ,0
Exp/Cntr=0.3,0.1

Type RM Length L Ch R = 1 ,3140.5  ,395.219,402.642,392.82
XS GIS Cut Line= 3
     1828460.404      354397.013     1828842.667      354643.473
     1829210.533      354912.902
#Sta/Elev= 30
       0 1390.55    48.4 1377.69    87.1 1362.99   106.4 1353.58   116.1    1351
   135.5 1341.54   183.9 1324.02   212.9 1304.06   222.6 1301.07   241.9 1291.28
   261.3 1284.67   280.6 1276.01   309.7 1268.71   358.1 1260.94   377.4 1254.74
   396.8 1244.34   406.4 1237.74   425.8 1220.53   435.5 1216.33   439.9 1216.57
   454.9  1220.1   474.2 1223.82   551.8 1225.82   561.5 1224.82   580.9 1218.35
   600.4 1217.05   639.2 1228.97     775 1235.04   862.3  1250.6   910.8 1263.99
#Mann= 3 , 0 , 0
       0      .1       0   439.9    .045       0   454.9      .1       0
#XS Ineff= 2 , 0
                          522.59         1225.38
Permanent Ineff=
       F       F
Bank Sta=439.9,454.9
XS Rating Curve= 0 ,0
Exp/Cntr=0.3,0.1

Type RM Length L Ch R = 1 ,2737.8  ,433.358,400,388.569
XS GIS Cut Line= 3
     1828324.201      354608.632     1828601.392       354955.12
     1829101.796      355092.463
#Sta/Elev= 30
       0 1363.92    28.9 1352.33    38.6  1347.8    57.9 1341.66    77.2 1332.95
    96.5 1327.32   144.7 1310.23   154.3 1307.93   173.6 1300.32   202.6 1292.05
   221.9 1287.28   260.4 1279.96     299 1269.88     328 1259.05   347.3 1249.94
   366.6 1242.41   385.8 1233.03   395.5 1229.49   414.8  1218.4   424.4 1213.93
   434.1 1212.38   436.2 1212.59   451.2 1214.14   561.2 1215.26   649.3 1217.23
   776.6 1223.09   845.1 1229.22   903.9  1236.4   943.1  1242.2   962.6  1246.9
#Mann= 3 , 0 , 0
       0      .1       0   436.2    .045       0   451.2      .1       0
Bank Sta=436.2,451.2
XS Rating Curve= 0 ,0
Exp/Cntr=0.3,0.1

Type RM Length L Ch R = 1 ,2337.8  ,424.544,429.502,428.438
XS GIS Cut Line= 3
     1828176.223      355527.757     1828564.977       355323.82
     1829095.554      355196.351
#Sta/Elev= 30
       0 1343.28     9.8  1337.4      39 1323.96    58.5 1320.44   107.3 1308.19
   136.6 1301.96   165.8 1294.89   214.6 1281.69   234.1 1278.24   282.9 1262.44
   302.4 1258.67   321.9 1253.79   331.7 1252.27   370.7 1236.46   390.2 1224.76
     400 1221.34   409.7 1211.95   419.5 1206.61   429.2    1206   431.5 1206.19
   446.5 1207.47   633.9 1209.97   692.3 1211.83   741.1 1214.88   770.3 1218.22
   809.3  1221.1   877.5 1227.91     936 1237.08   965.2 1242.91   984.7 1247.88
#Mann= 3 , 0 , 0
       0      .1       0   431.5    .045       0   446.5      .1       0
Bank Sta=431.5,446.5
XS Rating Curve= 0 ,0
Exp/Cntr=0.3,0.1

Type RM Length L Ch R = 1 ,1908.3  ,380.363,380.662,380.512
XS GIS Cut Line= 3
     1828414.027      355843.579     1828823.831      355600.404
     1829250.911      355449.393
#Sta/Elev= 30
       0 1367.93    19.4 1358.54    68.1 1339.23    97.2 1322.68   116.7  1314.8
   145.9 1308.62   165.3 1302.35   213.9 1290.15   272.3 1270.97     282 1269.71
   320.9 1258.15   340.4 1249.95   350.1 1247.72     389 1232.17   408.4 1220.44
   437.6 1209.52   447.3 1207.87   515.1 1203.67   534.5 1200.12     544 1198.62
   549.5 1198.84   563.3 1201.52   601.8 1216.49   746.4 1234.33   813.9 1246.81
   833.1 1252.48   842.8 1253.78     862 1260.01   910.2 1268.82   929.5 1273.91
#Mann= 3 , 0 , 0
       0      .1       0   534.5    .045       0   549.5      .1       0
Bank Sta=534.5,549.5
XS Rating Curve= 0 ,0
Exp/Cntr=0.3,0.1

Type RM Length L Ch R = 1 ,1527.7  ,461.327,458.39,455.904
XS GIS Cut Line= 3
     1828548.889      356093.272     1828980.057      355947.055
      1829415.87       355788.75
#Sta/Elev= 30
       0 1340.32     9.7 1335.99    19.4 1334.36    38.7 1326.78   106.6 1307.24
   145.3 1299.07   164.7 1293.72   174.4 1292.41   213.1 1281.58   232.5 1272.64
   242.2 1269.59   261.5  1259.8   271.2 1257.29   290.6 1246.25   319.7 1234.63
     339 1228.16   358.4 1219.47   406.9 1203.52   426.2 1194.48   446.2 1188.92
   455.3 1188.42   461.2 1189.19   522.9 1209.82   629.2  1215.5   735.4 1228.55
   764.4  1233.6   812.7 1245.99   841.7 1251.85   909.3 1264.48     919 1265.39
#Mann= 3 , 0 , 0
       0      .1       0   446.2    .045       0   461.2      .1       0
Bank Sta=446.2,461.2
XS Rating Curve= 0 ,0
Exp/Cntr=0.3,0.1

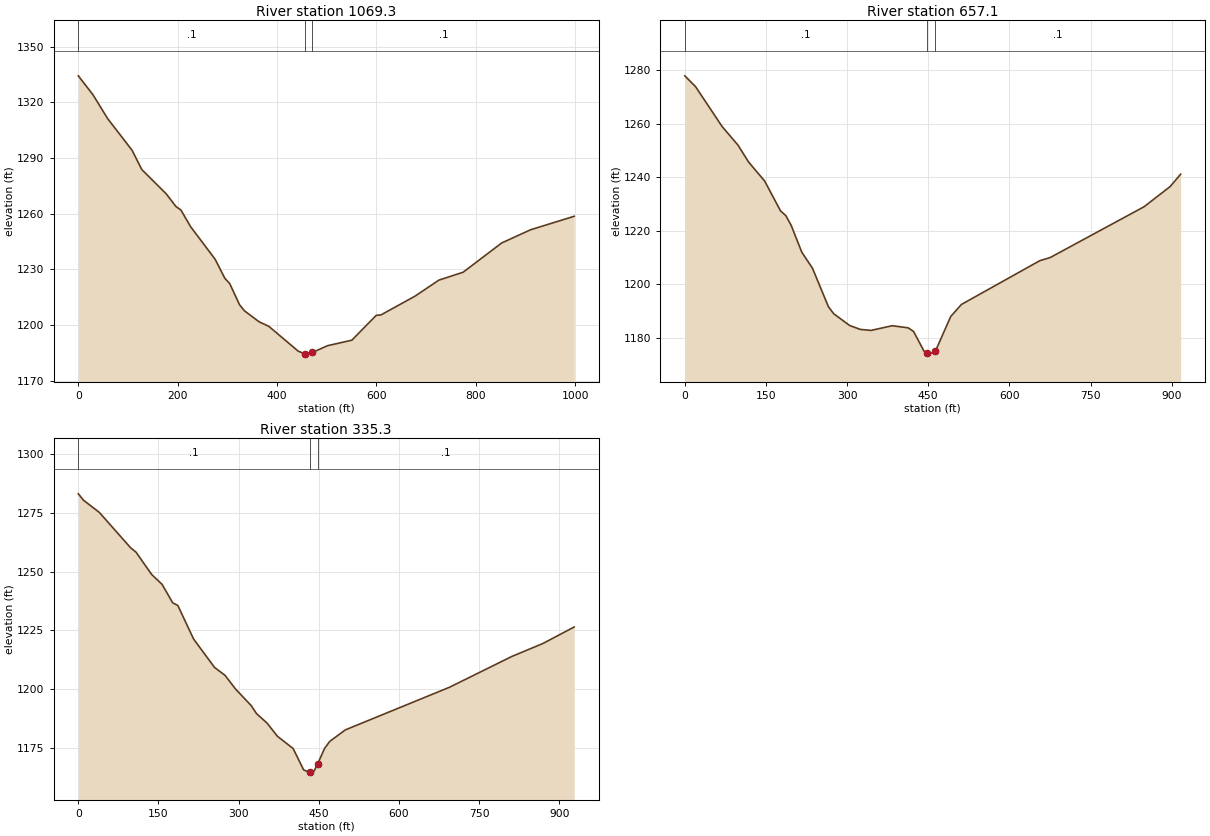
Type RM Length L Ch R = 1 ,1069.3  ,420.373,412.213,404.054
XS GIS Cut Line= 3
     1828778.275      356555.856     1829297.641      356297.674
     1829690.918      356156.574
#Sta/Elev= 30
       0 1334.23    29.5 1324.03      59  1311.2   108.1 1294.18   127.8 1283.75
   176.9  1270.7   196.6 1263.83   206.4    1262   226.1 1252.97   275.3 1235.49
   294.9 1225.22   304.7 1222.38   324.4 1211.01   334.2 1207.76   363.7 1201.84
   383.4 1199.37   442.4 1186.04   456.2 1184.51     462 1184.42   471.2 1185.34
   501.4 1188.95   550.5 1191.93   599.4 1205.28   609.1 1205.54   677.2 1215.57
   725.8 1224.28   774.3  1228.5   852.1 1244.28   910.4 1251.39   997.8 1258.62
#Mann= 3 , 0 , 0
       0      .1       0   456.2    .045       0   471.2      .1       0
Bank Sta=456.2,471.2
XS Rating Curve= 0 ,0
Exp/Cntr=0.3,0.1

Type RM Length L Ch R = 1 ,657.1   ,333.109,321.785,312.882
XS GIS Cut Line= 3
     1829138.529      357003.171     1829501.785      356615.898
     1829772.151      356340.884
#Sta/Elev= 30
       0 1277.84    19.7 1273.85    68.8 1258.95    98.3 1251.95     118 1245.61
   147.5 1238.57     177 1227.38   186.8 1225.59   196.7 1221.96   216.3 1211.93
     236 1205.96   265.5 1191.58   275.3 1188.94   304.8 1184.54   324.5 1183.09
   344.2 1182.71   383.5 1184.47     413 1183.67   422.8 1182.36   442.5 1174.87
   448.4 1174.26   452.3 1173.85   463.4    1175   491.6 1187.91   511.3  1192.4
   656.3 1208.77   675.6 1209.95   849.1 1228.93   897.3 1236.48   916.6 1241.07
#Mann= 3 , 0 , 0
       0      .1       0   448.4    .045       0   463.4      .1       0
Bank Sta=448.4,463.4
XS Rating Curve= 0 ,0
Exp/Cntr=0.3,0.1

Type RM Length L Ch R = 1 ,335.3   ,336.531,335.273,331.594
XS GIS Cut Line= 3
     1829559.111      357322.229      1829673.57      356885.859
     1829881.466      356456.637
#Sta/Elev= 30
       0 1283.02     9.8 1280.28    39.2 1275.16    98.1 1260.04   107.9 1258.26
   137.3 1248.75   156.9 1244.52   176.5 1236.76   186.3 1235.56   215.8 1221.32
     255 1209.26   274.6  1205.9   294.2  1200.1   323.6 1193.05   333.4 1189.67
   353.1 1185.65   372.7 1180.01   402.1  1174.8   421.7 1165.75   431.5 1164.78
   433.1 1164.86   441.3 1165.25   448.1 1168.34   460.9 1174.86   470.6 1177.84
   499.8 1182.73   694.5 1200.81   811.3 1213.91   869.7 1219.44   928.1 1226.44
#Mann= 3 , 0 , 0
       0      .1       0   433.1    .045       0   448.1      .1       0
Bank Sta=433.1,448.1
XS Rating Curve= 0 ,0
Exp/Cntr=0.3,0.1

Chan Stop Cuts=-1
Use User Specified Reach Order=0